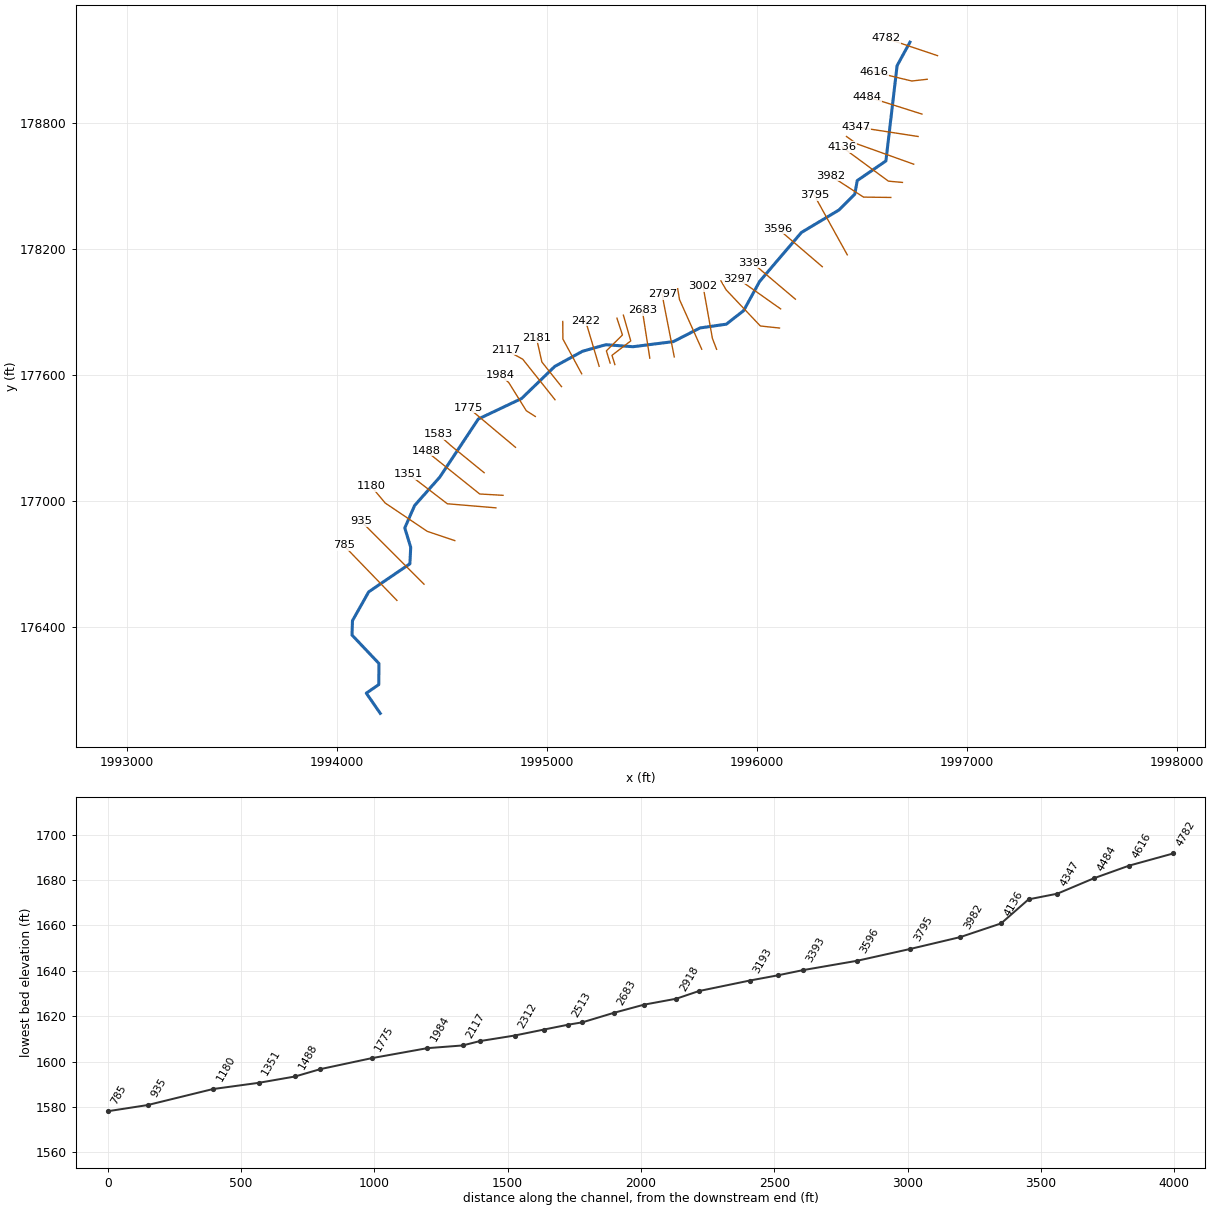
--- LKCKTRIB1.prj (project) ---

Proj Title=LKCKTRIB1
Current Plan=p01
Default Exp/Contr=0,0
English Units
Geom File=g01
Flow File=f01
Plan File=p01
BEGIN DESCRIPTION:
Stream Name: Lick Creek Tributary 1
Flood Zone: Approximate
Summers County, West Virginia
HEC-RAS Version: 5.0.7
Hydrology Method:
regression
Model Notes:
END DESCRIPTION:
DSS Export Rating Curves= 0
DSS Export Rating Curve Sorted= 0
DSS Export Volume Flow Curves= 0
DXF OffsetX= 0
DXF OffsetY= 0
DXF ScaleX= 0
DXF ScaleY= 0

--- LKCKTRIB1.p01 (plan) ---

Plan Title=Floodplain
Program Version=5.07
Short Identifier=Floodplain
Geom File=g01
Flow File=f01
Subcritical Flow
K Sum by GR= 0
Std Step Tol= 0.01
Critical Tol= 0.01
Num of Std Step Trials= 20
Max Error Tol= 0.3
Flow Tol Ratio= 0.001
Split Flow NTrial= 30
Split Flow Tol= 0.02
Split Flow Ratio= 0.02
Log Output Level= 0
Friction Slope Method= 1
Unsteady Friction Slope Method= 2
Unsteady Bridges Friction Slope Method= 1
Parabolic Critical Depth
Global Vel Dist= 0 , 0 , 0
Global Log Level= 0
CheckData=True
Encroach Param=-1 ,0,0, 0
Mapping Interval=1HOUR
Computation Time Step Use Courant=        0
Computation Time Step Use Time Series=    0
Computation Time Step Count To Double=0
Computation Time Step Max Doubling=0
Computation Time Step Max Halving=0
Computation Time Step Residence Courant=0
Run HTab= 0
Run UNet= 0
Run Sediment= 0
Run PostProcess= 0
Run WQNet= 0
Run RASMapper= 0
UNET Theta= 0
UNET Theta Warmup= 0
UNET ZTol= 0
UNET ZSATol= 0
UNET MxIter= 0
UNET Max Iter WO Improvement= 0
UNET MaxInSteps= 0
UNET DtIC= 0
UNET DtMin= 0
UNET MaxCRTS= 0
UNET WFStab= 0
UNET SFStab= 0
UNET WFX= 1
UNET SFX= 1
UNET 1D Methodology=Finite Difference
UNET DSS MLevel= 1
UNET Pardiso=0
UNET DZMax Abort= 0
UNET Use Existing IB Tables= 0
UNET Froude Reduction=False
UNET Froude Limit= 0
UNET Froude Power= 0
UNET D1 Cores= 0
UNET D2 Coriolis=0
UNET D2 Cores= 0
UNET D2 Theta= 1
UNET D2 Theta Warmup= 1
UNET D2 Z Tol= 0.01
UNET D2 Volume Tol= 0.01
UNET D2 Max Iterations= 20
UNET D2 Equation= 0
UNET D2 RampUpFraction=0.1
UNET D2 TimeSlices= 1
UNET D2 BCVolumeCheck=0
UNET D1D2 MaxIter= 0
UNET D1D2 ZTol=0.01
UNET D1D2 QTol=0.1
UNET D1D2 MinQTol=1
Write IC File= 0
Write IC File at Fixed DateTime=0
Write IC File at Sim End=0
Echo Input=False
Echo Parameters=False
Echo Output=False
Write Detailed= 0
HDF Write Warmup=0
HDF Write Time Slices=0
HDF Flush=0
HDF Face Node Velocities=0
HDF Compression= 1
HDF Chunk Size= 1
HDF Spatial Parts= 1
HDF Use Max Rows=0
HDF Fixed Rows= 1
Calibration Method= 0
Calibration Iterations= 20
Calibration Max Change=0.05
Calibration Tolerance=0.2
Calibration Maximum=1.5
Calibration Minimum=0.5
Calibration Optimization Method= 1
WQ AD Non Conservative
WQ ULTIMATE=-1
WQ Max Comp Step=1HOUR
WQ Output Interval=15MIN
WQ Output Selected Increments= 0
WQ Output face flow=0
WQ Output face velocity=0
WQ Output face area=0
WQ Output face dispersion=0
WQ Output cell volume=0
WQ Output cell surface area=0
WQ Output cell continuity=0
WQ Output cumulative cell continuity=0
WQ Output face conc=0
WQ Output face dconc_dx=0
WQ Output face courant=0
WQ Output face peclet=0
WQ Output face adv mass=0
WQ Output face disp mass=0
WQ Output cell mass=0
WQ Output cell source sink temp=0
WQ Output nsm pathways=0
WQ Output nsm derived pathways=0
WQ Output MaxMinRange=-1
WQ Daily Max Min Mean=-1
WQ Daily Range=0
WQ Daily Time=0
WQ Create Restart=0
WQ Fixed Restart=0
WQ System Summary=0
WQ Write To DSS=0
WQ Use Fixed Temperature=0
Sorting and Armoring Iterations= 10
XS Update Threshold= 0.02
Bed Roughness Predictor= 0
Hydraulics Update Threshold= 0.02
Energy Slope Method= 1
Volume Change Method= 1
Sediment Retention Method= 0
XS Weighting Method= 0
Number of US Weighted Cross Sections= 1
Number of DS Weighted Cross Sections= 1
Upstream XS Weight=0
Main XS Weight=1
Downstream XS Weight=0
Number of DS XS's Weighted with US Boundary= 1
Upstream Boundary Weight= 1
Weight of XSs Associated with US Boundary= 0
Number of US XS's Weighted with DS Boundary= 1
Downstream Boundary Weight= 0.5
Weight of XSs Associated with DS Boundary= 0.5
Percentile Method= 0
Sediment Output Level= 3
Mass or Volume Output= 0
Output Increment Type= 1
Profile and TS Output Increment= 1
XS Output Flag= 0
XS Output Increment= 10
Write Gradation File= 0
Read Gradation Hotstart= 0
Write HDF5 File= 1
Write Binary Output= 1
Write DSS Sediment File= 0
SV Curve= 0
Specific Gage Flag= 0

--- LKCKTRIB1.f01 (steady flow) ---

Flow Title=Flows
Program Version=5.07
Number of Profiles= 6
Profile Names=01pct,10pct,04pct,02pct,0_2pct,01plus
River Rch & RM=LKCKTRIB1,Main            ,4782
     474     249     332     401     665     702
River Rch & RM=LKCKTRIB1,Main            ,4616
     655     348     461     555     912     968
River Rch & RM=LKCKTRIB1,Main            ,2422
     737     393     520     625    1024    1090
Boundary for River Rch & Prof#=LKCKTRIB1,Main            , 1
Up Type= 0
Dn Type= 3
Dn Slope=0.023947
Boundary for River Rch & Prof#=LKCKTRIB1,Main            , 2
Up Type= 0
Dn Type= 3
Dn Slope=0.023947
Boundary for River Rch & Prof#=LKCKTRIB1,Main            , 3
Up Type= 0
Dn Type= 3
Dn Slope=0.023947
Boundary for River Rch & Prof#=LKCKTRIB1,Main            , 4
Up Type= 0
Dn Type= 3
Dn Slope=0.023947
Boundary for River Rch & Prof#=LKCKTRIB1,Main            , 5
Up Type= 0
Dn Type= 3
Dn Slope=0.023947
Boundary for River Rch & Prof#=LKCKTRIB1,Main            , 6
Up Type= 0
Dn Type= 3
Dn Slope=0.023947
DSS Import GetInterval= 0
DSS Import GetPeak= 0
DSS Import FillOption= 0

--- LKCKTRIB1.g01 (geometry) ---

Geom Title=Geometry
Program Version=5.07

River Reach=LKCKTRIB1       ,Main
Reach XY= 30
     1996727.865      179185.698     1996666.667      179073.979
1996613.34556379178620.188016166     1996476.833      178526.553
     1996465.114      178461.883     1996389.801      178386.515
1996210.73970858 178279.38257241     1996012.057      178046.553
     1995935.971      177907.504      1995853.34      177842.793
1995728.00136676177824.828108163     1995601.172      177759.779
     1995408.898      177735.474     1995279.558      177745.022
     1995168.447      177713.772     1995036.502      177641.724
     1994878.275      177488.698     1994672.142      177390.981
     1994488.759       177114.381994368.98971163 176979.29492133
     1994322.081      176872.441     1994350.304      176780.323
     1994346.398      176701.619     1994150.217      176567.939
      1994072.96      176430.786      1994070.79       176362.21
1994199.17439519176226.7215625141994198.20763612176126.263120441
1994138.86974779176085.618575219     1994205.345      175989.304

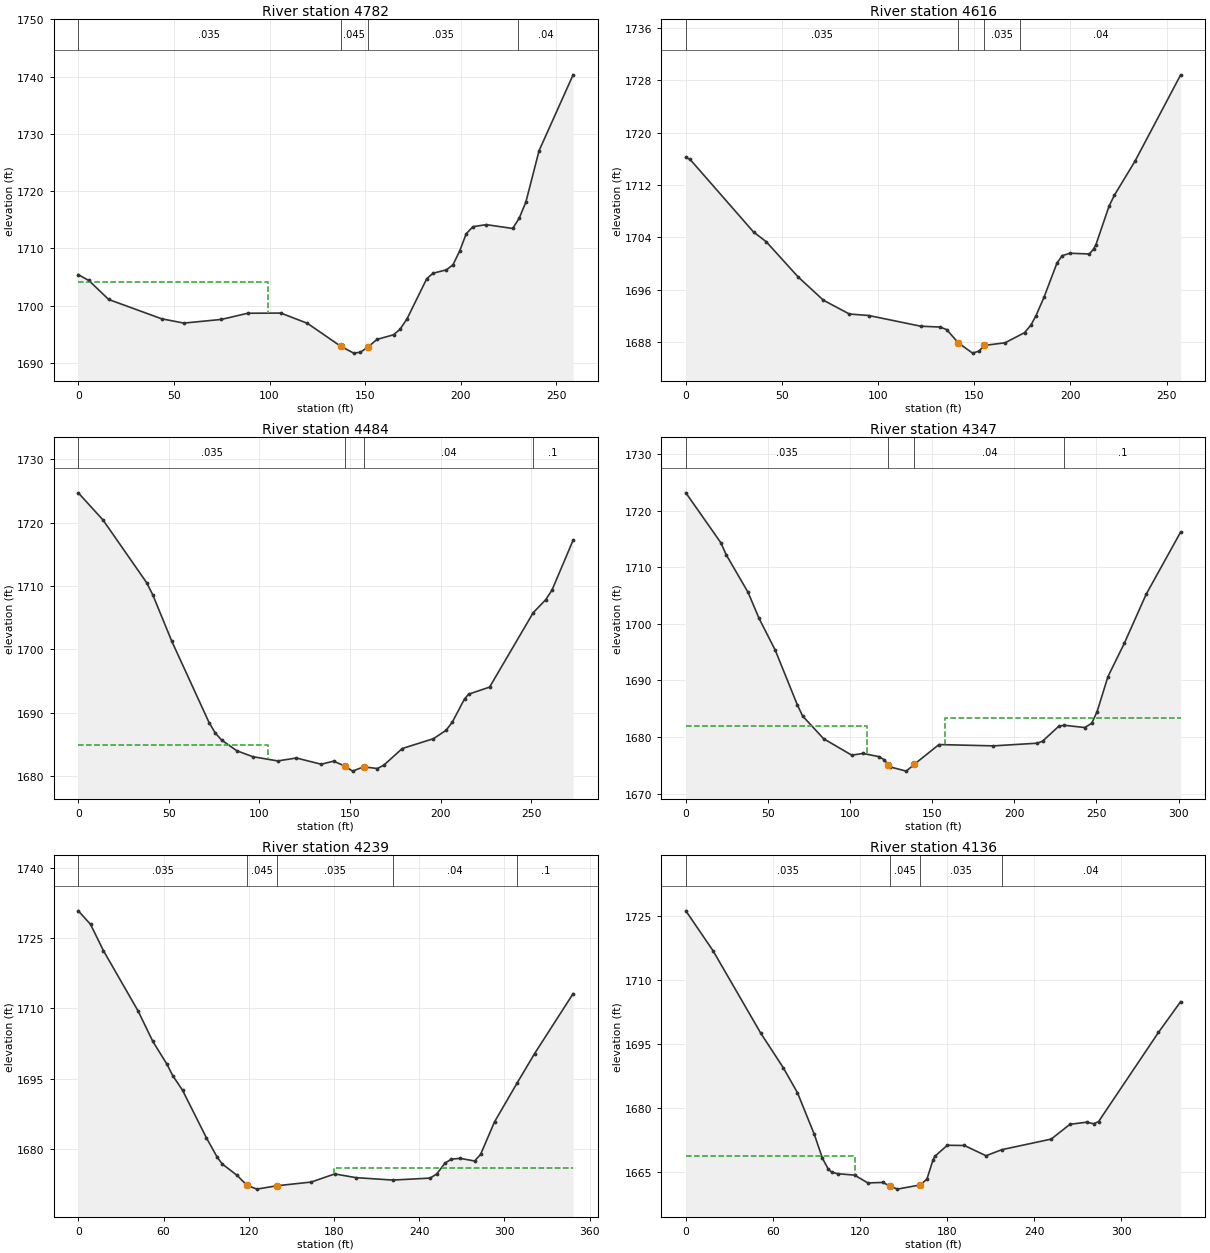
Type RM Length L Ch R = 1 ,4782    ,166.3,166.3,166.3
XS GIS Cut Line= 2
1996859.14780173179121.5931371151996613.92210728179204.058414891
#Sta/Elev= 30
       0 1705.43     5.5 1704.42    15.9  1701.1    43.6 1697.73    55.2 1696.98
    74.8 1697.62    88.6  1698.7   105.9 1698.73   119.8 1696.94   137.1 1692.96
     144 1691.74   147.5  1691.9   151.4 1692.79   156.2 1694.14   164.8 1694.94
   168.2  1695.9   171.8 1697.67   182.2 1704.74   185.5 1705.68   192.5 1706.28
   195.9 1707.16   199.4 1709.56   202.8 1712.56   206.3  1713.8   213.3 1714.16
   227.1 1713.49   230.5 1715.27     234 1718.09   240.9 1727.06   258.7  1740.3
#Mann= 4 ,-1 , 0
       0    .035       0   137.1    .045       0   151.4    .035       0
     230     .04       0
#XS Ineff= 2 , 0
           99.29 1704.14
Permanent Ineff=
       F       F
Bank Sta=137.1,151.4
XS Rating Curve= 0 ,0
Exp/Cntr(USF)=0,0
Exp/Cntr=0.3,0.1

Type RM Length L Ch R = 1 ,4616    ,132.3,131.8,131.2
XS GIS Cut Line= 3
1996810.10266286179009.1799426531996736.72332019179000.802582562
1996558.36655173179043.902164891
#Sta/Elev= 30
       0  1716.2     2.2 1715.91    35.2 1704.83    41.8 1703.35    58.3    1698
    71.5 1694.43      85 1692.32    95.1 1692.09   122.1 1690.46   132.2 1690.33
   135.6 1689.94   141.71687.912   149.1 1686.35   152.5 1686.67     1551687.514
     166 1687.93   176.1 1689.47   179.5 1690.65   182.1 1692.09   186.2 1694.85
     193 1700.11   195.7 1701.22   199.7 1701.59   209.8 1701.48     212 1702.24
   213.2 1702.87     220 1708.73   222.8 1710.43   233.5 1715.61   257.3 1728.81
#Mann= 4 ,-1 , 0
       0    .035       0   141.7    .045       0     155    .035       0
  173.86     .04       0
Bank Sta=141.7,155
XS Rating Curve= 0 ,0
Exp/Cntr(USF)=0,0
Exp/Cntr=0.3,0.1

Type RM Length L Ch R = 1 ,4484    ,135,137.2,137.6
XS GIS Cut Line= 2
1996784.92905173178843.3813315331996524.51238504178925.846609324
#Sta/Elev= 30
       0 1724.71    13.7 1720.41    37.8 1710.51    41.2 1708.57    51.6 1701.31
    72.2 1688.47    75.6 1686.83    79.1 1685.71    87.5 1684.02    96.3 1683.08
   110.1 1682.41   120.4 1682.87   134.1 1681.89     141 1682.37   147.21681.593
   151.4  1680.8   157.6 1681.48   165.1 1681.21   168.6 1681.72   178.9 1684.37
   196.1 1685.92     203 1687.23   206.4 1688.48   213.3 1692.22   215.6 1692.95
   227.1 1694.06   251.2 1705.81     258 1707.82   261.5 1709.34   273.2 1717.23
#Mann= 4 ,-1 , 0
       0    .035       0   147.2    .045       0   157.6     .04       0
   251.2      .1       0
#XS Ineff= 2 , 0
       0     105    1685               0
Permanent Ineff=
       F       F
Bank Sta=147.2,157.6
XS Rating Curve= 0 ,0
Exp/Cntr(USF)=0,0
Exp/Cntr=0.3,0.1

Type RM Length L Ch R = 1 ,4347    ,112.3,108.1,106.4
XS GIS Cut Line= 2
1996766.69988507178736.6104982051996468.95682952178782.617442653
#Sta/Elev= 30
       0 1723.12    21.3 1714.31    24.6 1712.18    37.9 1705.54    44.6 1700.94
    54.5  1695.3    67.8 1685.75    71.1 1683.72    83.9 1679.71     101 1676.81
   107.8 1677.11   117.6 1676.55   120.9 1675.97   123.2 1675.13   124.2 1674.75
   134.2 1673.99   139.11675.195   154.1 1678.68   187.3 1678.45   213.9 1678.92
   217.2 1679.27   227.2 1681.95   230.5 1682.08   242.9 1681.69   247.1 1682.43
   250.4 1684.49     257 1690.66     267 1696.57   280.3 1705.22   301.3 1716.21
#Mann= 4 ,-1 , 0
       0    .035       0   123.2    .045       0   139.1     .04       0
   230.5      .1       0
#XS Ineff= 2 , 0
           110.5    1682  157.76         1683.37
Permanent Ineff=
       F       F
Bank Sta=123.2,139.1
XS Rating Curve= 0 ,0
Exp/Cntr(USF)=0,0
Exp/Cntr=0.3,0.1

Type RM Length L Ch R = 1 ,4239    ,109.2,103,101
XS GIS Cut Line= 3
 1996745.8665517178604.6660537571996474.16516283178701.888275996
1996425.55405173178736.610498205
#Sta/Elev= 30
       0 1730.79     8.6 1727.92    17.7 1722.31    42.1 1709.45    52.5 1702.95
    62.5 1698.06    66.5 1695.67    73.4 1692.55    90.2 1682.42    97.8 1678.29
   101.3 1676.86   111.8 1674.42   118.7 1672.31   125.7 1671.49   139.6  1672.2
     164    1673   180.5 1674.73   195.4 1673.94   221.4 1673.42   247.7 1673.84
   252.4 1674.75   258.1 1677.03   262.6 1677.87   268.6 1678.05     279 1677.49
   283.2 1678.91     293 1685.83   309.1 1694.21   321.2 1700.37   348.3 1713.14
#Mann= 5 ,-1 , 0
       0    .035       0   118.7    .045       0   139.6    .035       0
   221.4     .04       0   309.1      .1       0
#XS Ineff= 2 , 0
       0                     180       0    1676
Permanent Ineff=
       F       F
Bank Sta=118.7,139.6
XS Rating Curve= 0 ,0
Exp/Cntr(USF)=0,0
Exp/Cntr=0.3,0.1

Type RM Length L Ch R = 1 ,4136    ,151.1,153.2,151.3
XS GIS Cut Line= 3
1996692.04710731178517.8604982051996625.20682949  178523.9368871
1996404.72071838178686.263275981
#Sta/Elev= 30
       0 1726.13    18.7 1716.79    51.6 1697.45    67.1 1689.36    76.9 1683.49
    88.5 1673.73    94.1 1668.12      98 1665.66   100.4 1664.88   104.6  1664.5
   116.2 1664.18   125.4 1662.34   135.6 1662.46   140.3 1661.69   145.7 1660.89
   161.51661.882   166.1 1663.24   170.2 1667.67   171.5 1668.57   180.1 1671.17
   191.9 1671.12   206.8 1668.72   217.7 1670.14   251.7 1672.62   264.6 1676.08
   276.1 1676.58     281 1676.22   284.3 1676.71   325.6 1697.63   340.9 1704.85
#Mann= 4 ,-1 , 0
       0    .035       0   140.3    .045       0   161.5    .035       0
   217.7     .04       0
#XS Ineff= 2 , 0
          116.46 1668.77
Permanent Ineff=
       F       F
Bank Sta=140.3,161.5
XS Rating Curve= 0 ,0
Exp/Cntr(USF)=0,0
Exp/Cntr=0.3,0.1

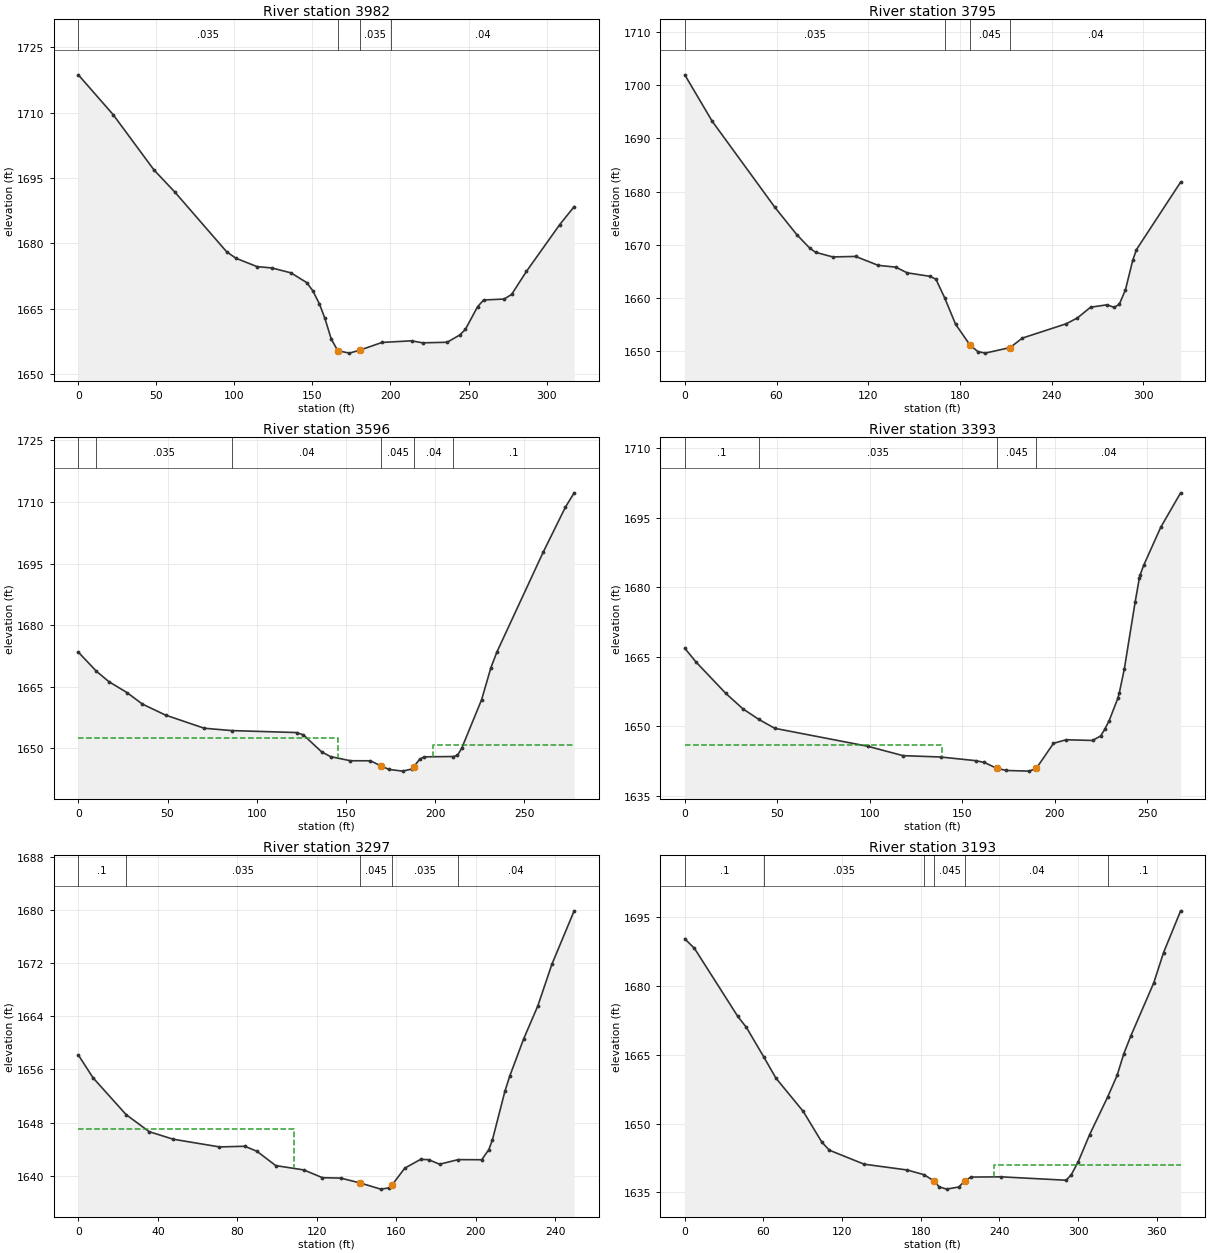
Type RM Length L Ch R = 1 ,3982    ,194,187.4,180.1
XS GIS Cut Line= 3
1996636.68024722178446.2787497161996506.64487024178447.927893027
 1996349.2465623178550.083926677
#Sta/Elev= 30
       0 1718.64    22.3 1709.52    48.5 1696.83    61.7 1691.83      95  1678.1
     101  1676.6   114.5 1674.69     124 1674.38   136.3 1673.25   146.3 1671.03
   150.2 1669.18   154.4  1666.2     158 1662.82     162 1658.15   166.21655.423
   173.7 1654.86   180.4 1655.55   194.6 1657.31   213.5 1657.68   220.6 1657.22
   236.3 1657.35   244.4 1659.02     248  1660.3   255.8 1665.49   259.7 1667.04
   272.8 1667.25   277.6  1668.3   287.1 1673.58   308.4 1684.29   317.7 1688.43
#Mann= 4 ,-1 , 0
       0    .035       0   166.2    .045       0   180.4    .035       0
  200.05     .04       0
Bank Sta=166.2,180.4
XS Rating Curve= 0 ,0
Exp/Cntr=0.3,0.1

Type RM Length L Ch R = 1 ,3795    ,193.6,199.5,204.6
XS GIS Cut Line= 2
1996429.33268303178173.0614105031996272.32940505178456.916095069
#Sta/Elev= 30
       0 1701.94    17.9 1693.23    58.9 1677.06    73.4 1671.86    81.8 1669.36
    85.6 1668.58    96.8 1667.72   111.8 1667.81   126.5 1666.14     138  1665.8
   145.5 1664.73   160.5 1664.07   164.3 1663.53     170 1660.05   177.2 1655.05
   186.71651.127   191.7 1649.94   196.5 1649.64   212.81650.684   220.9 1652.47
   249.6 1655.16   256.9 1656.26   265.5 1658.27   276.2 1658.72     281 1658.24
   284.3 1658.83   288.3 1661.54   293.1 1667.12   295.5 1669.09   324.4 1681.78
#Mann= 4 ,-1 , 0
       0    .035       0     170     .04       0   186.7    .045       0
   212.8     .04       0
Bank Sta=186.7,212.8
XS Rating Curve= 0 ,0
Exp/Cntr=0.3,0.1

Type RM Length L Ch R = 1 ,3596    ,202.3,202.6,202.4
XS GIS Cut Line= 2
1996310.32002136178116.6143234231996099.23934484178297.337164305
#Sta/Elev= 30
       0 1673.41    10.1 1668.77    17.1 1666.23    27.3 1663.55    35.9 1660.76
    48.9 1658.07    70.6 1654.87    85.9  1654.3   122.3 1653.82   126.2 1653.24
   136.3 1649.14   141.4 1647.95   152.5 1646.95   163.7 1646.94   169.71645.673
   174.1 1644.84   181.7 1644.42   186.8 1644.92   188.11645.545   191.4 1647.35
   193.9  1647.9   210.2 1647.98   212.5 1648.26   214.9 1650.03     226  1661.8
   231.2 1669.57   234.6 1673.45   260.5 1697.73     273 1708.74   277.9 1712.23
#Mann= 6 ,-1 , 0
       0      .1       0    10.1    .035       0    85.9     .04       0
   169.7    .045       0   188.1     .04       0   210.2      .1       0
#XS Ineff= 2 , 0
          145.34 1652.38  198.59         1650.85
Permanent Ineff=
       F       F
Bank Sta=169.7,188.1
XS Rating Curve= 0 ,0
Exp/Cntr=0.3,0.1

Type RM Length L Ch R = 1 ,3393    ,94.1,95.6,96.8
XS GIS Cut Line= 2
1996182.32713553177961.8891935391995977.68183239178134.739949057
#Sta/Elev= 30
       0 1666.83       6 1663.88    22.1 1657.11    31.4 1653.75      40 1651.47
    48.6 1649.55    98.9 1645.67   117.9 1643.65   138.2 1643.36   157.1 1642.57
   161.8 1642.19   168.51640.933   173.8 1640.45     186 1640.31   189.91640.893
   199.2  1646.3     206 1647.08   220.3 1646.93   224.7 1647.91     227 1649.41
   229.3 1651.22     234 1656.06   234.8 1657.24   237.5  1662.4   243.3 1676.73
   245.6 1681.96   246.1 1682.73   247.9 1684.68   257.2 1692.97   267.9 1700.36
#Mann= 4 ,-1 , 0
       0      .1       0      40    .035       0   168.5    .045       0
   189.9     .04       0
#XS Ineff= 2 , 0
             139    1646
Permanent Ineff=
       F       F
Bank Sta=168.5,189.9
XS Rating Curve= 0 ,0
Exp/Cntr=0.3,0.1

Type RM Length L Ch R = 1 ,3297    ,107.4,104.9,100
XS GIS Cut Line= 2
1996111.99474967 177915.552872341995908.30983361178059.410443233
#Sta/Elev= 30
       0 1658.18     7.4 1654.74      24 1649.21    35.6 1646.64    47.7  1645.5
      71 1644.34    83.8 1644.44    89.9 1643.67    99.3 1641.53   113.4 1640.88
   122.8 1639.71     132 1639.65   141.91638.906   152.1 1637.99   156.1 1638.16
   157.91638.655   164.2 1641.15   172.2 1642.47   176.2 1642.42   181.7 1641.74
   191.1 1642.43   202.9 1642.41   206.5 1643.95   208.3 1645.41   214.6 1652.75
     217    1655     224  1660.6   231.1 1665.54   238.2 1671.82   249.4 1679.86
#Mann= 5 ,-1 , 0
       0      .1       0      24    .035       0   141.9    .045       0
   157.9    .035       0   191.1     .04       0
#XS Ineff= 2 , 0
           108.5    1647
Permanent Ineff=
       F       F
Bank Sta=141.9,157.9
XS Rating Curve= 0 ,0
Exp/Cntr(USF)=0,0
Exp/Cntr=0.3,0.1

Type RM Length L Ch R = 1 ,3193    ,198.1,190.6,181.3
XS GIS Cut Line= 4
1996106.66490674177824.3637676951996015.36576188177834.237856952
1995852.49345024178006.2826190331995827.65408841178049.132849344
#Sta/Elev= 30
       0 1690.29     7.4 1688.19    40.4 1673.38      47 1670.97    60.2 1664.56
    69.5 1659.92    90.4 1652.64   104.6 1645.93   110.3 1644.19   136.8 1641.14
   169.6 1639.88   182.6 1638.84   190.5 1637.41     194 1636.21   199.8  1635.7
   209.1 1636.17   213.71637.532   218.3 1638.33   241.5 1638.38     291 1637.64
   294.9 1638.86   300.1 1641.63   308.8 1647.54   322.7 1655.84   329.8 1660.48
     335 1665.27   340.3 1669.11   357.8 1680.68   365.3  1687.3   378.3 1696.39
#Mann= 6 ,-1 , 0
       0      .1       0    60.2    .035       0   182.6     .04       0
   190.5    .045       0   213.7     .04       0   322.7      .1       0
#XS Ineff= 2 , 0
                             236            1641
Permanent Ineff=
       F       F
Bank Sta=190.5,213.7
XS Rating Curve= 0 ,0
Exp/Cntr=0.3,0.1

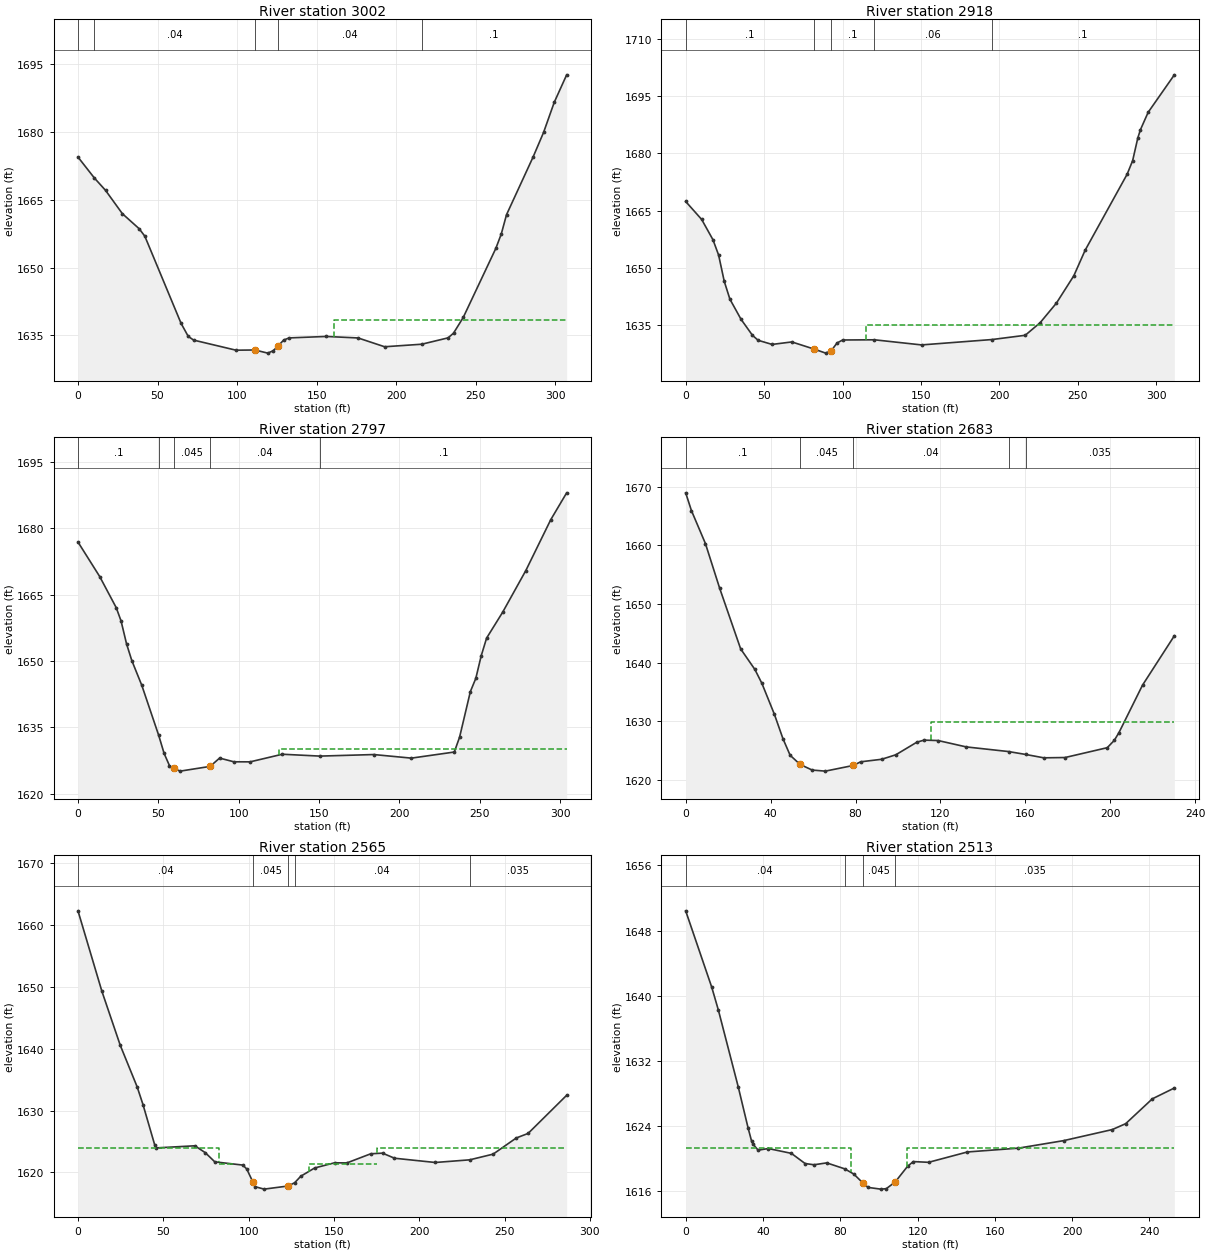
Type RM Length L Ch R = 1 ,3002    ,81.2,84.2,87
XS GIS Cut Line= 3
1995807.07290597177723.2060726781995787.12521956177774.984788919
1995742.74791401 178022.66093805
#Sta/Elev= 30
       0 1674.46    10.3 1669.83    17.3  1667.1    27.9 1661.93    38.4 1658.62
      42 1656.96    64.8 1637.65    69.3 1634.77    72.7 1633.95    99.3 1631.72
   111.21631.763   119.3 1631.07   122.7 1631.61   125.51632.577   129.3 1633.97
   132.7 1634.44     156 1634.76     176 1634.43   192.7 1632.48     216 1633.04
   232.6 1634.45     236 1635.49   242.1 1638.96   262.6 1654.26     266 1657.42
   269.3  1661.7     286 1674.47   292.6 1679.92   299.3 1686.58   307.1 1692.66
#Mann= 5 ,-1 , 0
       0      .1       0    10.3     .04       0   111.2    .045       0
   125.5     .04       0     216      .1       0
#XS Ineff= 2 , 0
                          161.18         1638.38
Permanent Ineff=
       F       F
Bank Sta=111.2,125.5
XS Rating Curve= 0 ,0
Exp/Cntr=0.3,0.1

Type RM Length L Ch R = 1 ,2918    ,124,121,117.4
XS GIS Cut Line= 3
1995736.35410959177723.5173268911995630.45133182177959.628438011
1995621.77077624178011.711771339
#Sta/Elev= 30
       0 1667.42    10.2 1662.71    17.4  1657.4      21 1653.39    24.6 1646.51
    28.2 1641.84    35.3 1636.57    42.6 1632.37    46.2 1631.07    55.1 1629.99
    67.7 1630.64    82.1 1628.74    89.3 1627.71    92.9 1628.39    96.5 1630.36
   100.1 1631.15   120.4  1631.2   150.4 1629.86   195.4 1631.27   216.5 1632.38
     226 1635.67   236.4 1640.81   247.5 1647.97   254.7 1654.64   281.5 1674.56
     285 1678.11   288.3 1684.06     290 1686.24   294.9 1690.77   311.6 1700.58
#Mann= 5 ,-1 , 0
       0      .1       0    82.1    .045       0    92.9      .1       0
   120.4     .06       0   195.4      .1       0
#XS Ineff= 2 , 0
       0                     115       0    1635
Permanent Ineff=
       F       F
Bank Sta=82.1,92.9
XS Rating Curve= 0 ,0
Exp/Cntr(USF)=0,0
Exp/Cntr=0.3,0.1

Type RM Length L Ch R = 1 ,2797    ,114.2,113.5,113.2
XS GIS Cut Line= 3
1995605.45396302177686.8071681351995555.15398271177944.051776044
1995548.39529694177985.358980482
#Sta/Elev= 30
       0 1676.92    13.5 1669.12    23.8 1662.07    26.8 1659.07    30.2  1653.9
    33.5 1650.09    39.7  1644.5    50.2  1633.2    53.6 1629.08    56.9 1626.35
    59.51625.715    63.6 1625.09    82.2 1626.16    88.1 1628.04      97  1627.2
   107.1 1627.19   127.1 1628.91   150.5 1628.49     184 1628.84   207.4 1628.03
   234.1 1629.41   237.4 1632.78   244.1 1643.09   247.5 1646.09   250.8 1651.13
   254.2 1655.19   264.2 1661.05   278.6 1670.47   294.1 1681.97     304 1688.05
#Mann= 5 ,-1 , 0
       0      .1       0    50.2     .04       0    59.5    .045       0
    82.2     .04       0   150.5      .1       0
#XS Ineff= 2 , 0
       0                     125       0    1630
Permanent Ineff=
       F       F
Bank Sta=59.5,82.2
XS Rating Curve= 0 ,0
Exp/Cntr=0.3,0.1

Type RM Length L Ch R = 1 ,2683    ,134.2,117.9,100.1
XS GIS Cut Line= 2
1995488.95827624177680.9826046531995453.36799845177908.413160235
#Sta/Elev= 30
       0 1668.97     2.7 1665.95     9.3 1660.32      16  1652.7    25.9 1642.34
    32.6 1638.83    35.9 1636.46    41.8 1631.17    45.8 1627.04    49.2 1624.19
    53.9 1622.62    59.6 1621.66    65.8 1621.48      79 1622.45    82.4 1623.07
    92.3  1623.5      99 1624.27   108.9 1626.42   112.3 1626.77   118.9  1626.7
   132.2 1625.61   152.1 1624.82   160.1 1624.33   168.7 1623.75   178.7  1623.8
   198.6 1625.48   201.9 1626.73   204.1 1628.05   215.2 1636.15   230.2 1644.58
#Mann= 5 ,-1 , 0
       0      .1       0    53.9    .045       0      79     .04       0
   152.1      .1       0   160.1    .035       0
#XS Ineff= 2 , 0
                          115.79         1629.85
Permanent Ineff=
       F       F
Bank Sta=53.9,79
XS Rating Curve= 0 ,0
Exp/Cntr(USF)=0,0
Exp/Cntr=0.5,0.3

Type RM Length L Ch R = 1 ,2565    ,49.2,52.1,58.4
XS GIS Cut Line= 4
1995322.56108613177650.5255481051995308.88054236177694.462239753
1995398.25313548177763.0068823531995363.12448544177885.832246744
#Sta/Elev= 30
       0 1662.32      14 1649.32    24.8 1640.55    34.7 1633.83    38.1 1630.98
      45 1624.43      46 1623.97    68.5 1624.31    74.6  1623.2    80.2 1621.71
    96.6 1621.19    98.9 1620.56   102.61618.401   103.7  1617.7   109.1  1617.3
   123.21617.806     127 1618.34   130.6 1619.39   138.7 1620.72   150.4 1621.56
   157.6 1621.54   171.6 1623.02   178.5 1623.12   185.5  1622.3   209.4 1621.61
   229.6 1622.04   243.3 1622.96   256.9 1625.58   263.8 1626.31   286.4 1632.48
#Mann= 5 ,-1 , 0
       0     .04       0   102.6    .045       0   123.2    .035       0
     127     .04       0   229.6    .035       0
#XS Ineff= 4 ,-1
       0    82.9    1624    82.9    90.6  1621.4   135.2     175  1621.4
     175   286.3    1624
Permanent Ineff=
       F       F       F       F
Bank Sta=102.6,123.2
XS Rating Curve= 0 ,0
Exp/Cntr(USF)=0,0
Exp/Cntr=0.5,0.3

Type RM Length L Ch R = 1 ,2513    ,76,91.5,104.4
XS GIS Cut Line= 4
1995300.06333607 177657.632279151995282.16884956 177715.78096705
1995358.76004014177791.4752400291995332.32008263177871.564092236
#Sta/Elev= 30
       0 1650.43    13.5 1641.05    16.9 1638.27    27.2 1628.83    32.3 1623.79
    34.1 1622.18    34.9 1621.79    37.5 1621.06    42.8 1621.26    54.7 1620.67
    61.8 1619.42    66.4 1619.27      73  1619.5    82.3 1618.77      87 1618.13
    91.91616.992    94.4 1616.49   100.9 1616.28   103.8 1616.33   108.4 1617.15
   114.8 1619.07   117.8 1619.66   125.7 1619.57   145.8 1620.84   172.2 1621.31
   195.6 1622.23   220.8 1623.59   227.7 1624.31   241.5 1627.36   252.9 1628.69
#Mann= 4 ,-1 , 0
       0     .04       0    82.3    .035       0    91.9    .045       0
   108.4    .035       0
#XS Ineff= 2 , 0
            85.3  1621.3   114.7          1621.3
Permanent Ineff=
       F       F
Bank Sta=91.9,108.4
XS Rating Curve= 0 ,0
Exp/Cntr(USF)=0,0
Exp/Cntr=0.5,0.3

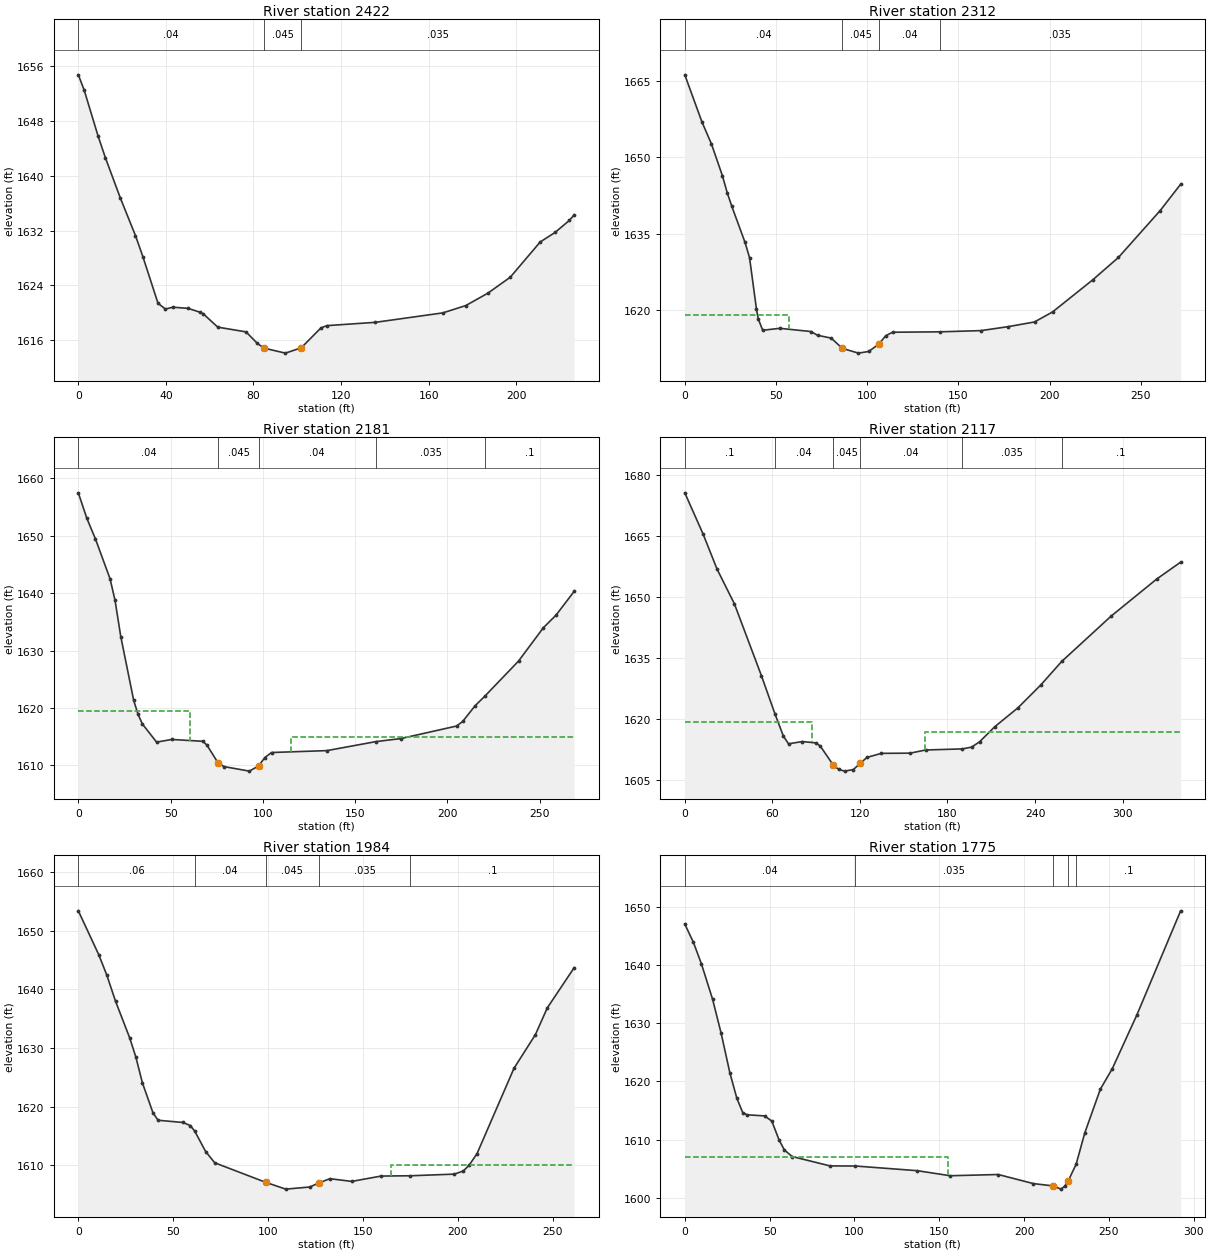
Type RM Length L Ch R = 1 ,2422    ,107.2,110,113
XS GIS Cut Line= 2
1995247.61089188177642.2122578171995182.92529011177859.281215772
#Sta/Elev= 30
       0 1654.73     2.7 1652.47       9 1645.82    12.4  1642.6    19.2 1636.75
    26.1 1631.28    29.5 1628.19    36.4  1621.4    39.8 1620.56    43.2 1620.83
    50.1 1620.66    55.5 1620.11    56.9 1619.91    63.7 1617.92    76.6 1617.23
    81.8 1615.54    84.9 1614.85    94.6 1614.13   101.81614.902   110.8  1617.8
   113.5 1618.14   135.6 1618.62   166.5    1620     177 1621.07     187 1622.86
   197.3  1625.2     211 1630.35   217.8 1631.74   224.3 1633.49   226.5  1634.3
#Mann= 3 ,-1 , 0
       0     .04       0    84.9    .045       0   101.8    .035       0
Bank Sta=84.9,101.8
XS Rating Curve= 0 ,0
Exp/Cntr(USF)=0,0
Exp/Cntr=0.3,0.1

Type RM Length L Ch R = 1 ,2312    ,128,131.2,133.4
XS GIS Cut Line= 3
1995164.63097042177606.4155678521995075.10258258 177772.04308535
1995074.35651268177855.602913998
#Sta/Elev= 30
       0 1666.24     9.4 1656.97    14.6 1652.65    20.6 1646.41    23.3 1642.99
    25.8 1640.34      33 1633.29    35.5 1630.26    39.3 1620.11    40.3  1618.2
    42.7 1615.99    52.1 1616.37    69.1 1615.74    72.8    1615    80.3 1614.44
    86.3 1612.43    95.2 1611.49   100.8 1611.82   106.4 1613.27   110.1  1614.9
   113.9  1615.6     140 1615.68   162.4 1615.92   177.3  1616.7   191.7 1617.62
   201.6 1619.59   223.6  1625.9   237.7 1630.31   260.6 1639.54   271.8 1644.71
#Mann= 4 ,-1 , 0
       0     .04       0    86.3    .045       0   106.4     .04       0
     140    .035       0
#XS Ineff= 2 , 0
       0   57.23 1619.06               0
Permanent Ineff=
       F       F
Bank Sta=86.3,106.4
XS Rating Curve= 0 ,0
Exp/Cntr(USF)=0,0
Exp/Cntr=0.3,0.1

Type RM Length L Ch R = 1 ,2181    ,63.2,64.1,63.5
XS GIS Cut Line= 3
1995068.37085518177545.5194662991994974.83250838177662.838967545
1994948.97238032177778.630774363
#Sta/Elev= 30
       0 1657.45     4.6 1653.02     9.3  1649.4    17.2 1642.48    19.9 1638.72
      23 1632.44      30 1621.33    32.4 1618.88    34.7 1617.23    42.4 1614.07
    50.7 1614.53    67.5 1614.21    69.7 1613.55    75.9 1610.36    79.1  1609.8
    92.7 1609.02    97.7 1609.93   101.1 1611.39   104.7 1612.26   134.7 1612.59
   161.3 1614.16   174.7 1614.68     205 1616.87   208.3 1617.67     215 1620.39
   220.4  1622.1   238.6 1628.19     252 1633.97   258.9 1636.17   268.7 1640.31
#Mann= 5 ,-1 , 0
       0     .04       0    75.9    .045       0    97.7     .04       0
   161.3    .035       0   220.4      .1       0
#XS Ineff= 2 , 0
       0   60.69 1619.45     115       0    1615
Permanent Ineff=
       F       F
Bank Sta=75.9,97.7
XS Rating Curve= 0 ,0
Exp/Cntr=0.3,0.1

Type RM Length L Ch R = 1 ,2117    ,135.3,133,130.4
XS GIS Cut Line= 3
1995037.52598459177483.1527435331994883.44612342177676.295104653
1994802.06591508177720.782951877
#Sta/Elev= 30
       0 1675.71    12.5 1665.58    22.1 1656.91      34 1648.34    52.5 1630.65
    61.8 1621.21    67.6 1615.71    71.1 1613.84    80.5  1614.4    89.8 1614.07
    92.8 1613.32   101.5 1608.73   105.4 1607.53   109.6 1607.11   115.5  1607.5
   120.2 1609.01   124.8 1610.49   134.7 1611.49   154.5 1611.54     165 1612.32
   190.2 1612.59   196.6 1613.03     202 1614.34   212.4 1618.05   228.2 1622.68
   243.9 1628.32   258.3 1634.14   292.1  1645.3   323.4 1654.46   339.8 1658.62
#Mann= 6 ,-1 , 0
       0      .1       0    61.8     .04       0   101.5    .045       0
   120.2     .04       0   190.2    .035       0   258.3      .1       0
#XS Ineff= 2 , 0
           86.96  1619.3  164.91          1616.8
Permanent Ineff=
       F       F
Bank Sta=101.5,120.2
XS Rating Curve= 0 ,0
Exp/Cntr(USF)=0,0
Exp/Cntr=0.3,0.1

Type RM Length L Ch R = 1 ,1984    ,207.8,208.9,210.2
XS GIS Cut Line= 4
 1994943.6957527177403.2417805711994900.65956195177430.783266733
1994817.29153827177564.6918298191994778.37017052177599.889912997
#Sta/Elev= 30
       0 1653.39    10.8 1645.88      15 1642.43    19.6 1637.97    27.1 1631.69
    30.3 1628.45    33.8 1624.01    39.3 1618.97      42 1617.66    55.2 1617.28
    59.1 1616.74    61.4 1615.77    67.1 1612.32    71.9  1610.4    98.71607.076
   109.3 1605.91   121.9 1606.27   126.71606.948   132.5 1607.69   144.1 1607.23
   159.6 1608.14     175 1608.19   198.2 1608.47   202.9 1609.01   205.9 1609.97
   210.1 1611.96   229.6 1626.53   240.9 1632.28   247.1 1636.81   261.3 1643.69
#Mann= 5 ,-1 , 0
       0     .06       0    61.4     .04       0    98.7    .045       0
   126.7    .035       0     175      .1       0
#XS Ineff= 2 , 0
                             165            1610
Permanent Ineff=
       F       F
Bank Sta=98.7,126.7
XS Rating Curve= 0 ,0
Exp/Cntr=0.3,0.1

Type RM Length L Ch R = 1 ,1775    ,192.1,191.8,191.7
XS GIS Cut Line= 2
1994849.26240449177256.4409013941994625.36311909177444.318452664
#Sta/Elev= 30
       0 1647.03     5.1 1643.87     9.8 1640.19    16.4 1634.09    21.4  1628.3
    26.6 1621.43    30.7 1617.09    34.2 1614.61    36.8 1614.26      47 1614.07
    51.3 1613.18    55.6 1609.92    58.7 1608.22    63.3 1607.09    85.6 1605.48
   100.6 1605.46     137 1604.66   156.5 1603.79   184.8    1604   205.5 1602.44
   217.31602.036   221.7 1601.49     224    1602   226.11602.947   230.7 1605.77
   235.8 1611.15     245 1618.68     252 1622.17   266.5 1631.41   292.3  1649.3
#Mann= 5 ,-1 , 0
       0     .04       0   100.6    .035       0   217.3    .045       0
   226.1    .035       0   230.7      .1       0
#XS Ineff= 2 , 0
       0     155    1607               0
Permanent Ineff=
       F       F
Bank Sta=217.3,226.1
XS Rating Curve= 0 ,0
Exp/Cntr=0.3,0.1

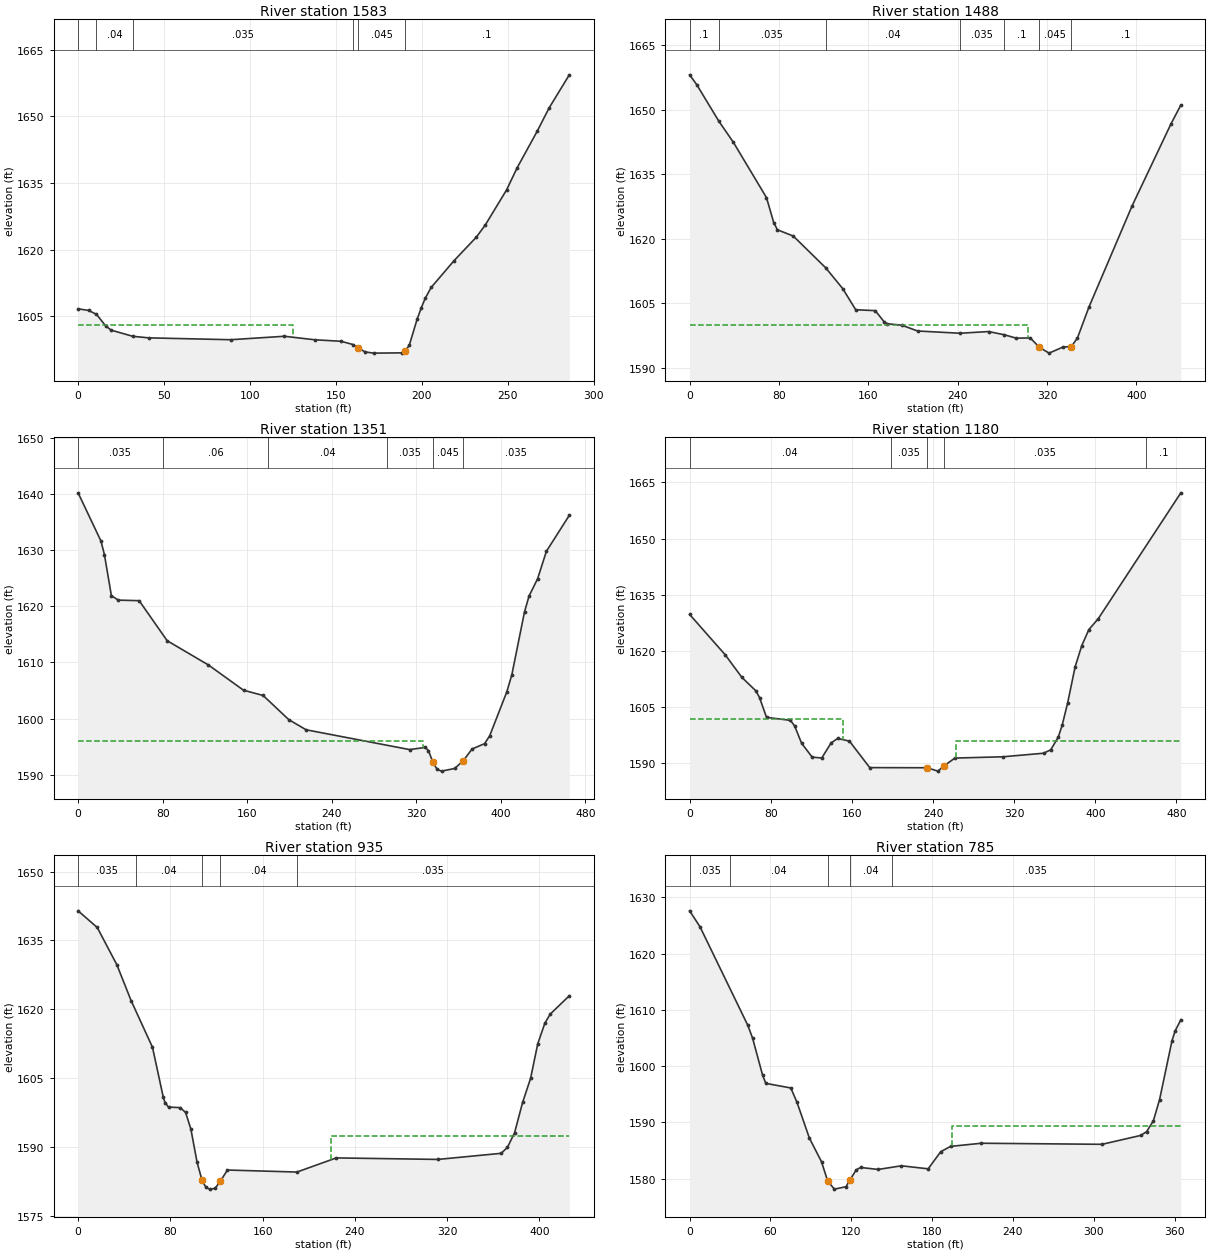
Type RM Length L Ch R = 1 ,1583    ,94.3,94.6,94.4
XS GIS Cut Line= 3
1994700.11430349177135.4293141881994543.17654035177263.256183183
1994480.76849398177318.522653636
#Sta/Elev= 30
       0 1606.66     6.1  1606.3    10.7 1605.42      16 1602.84    19.2 1601.86
    31.8 1600.47    41.1 1600.12    88.8  1599.7     120 1600.48   137.6 1599.69
     153 1599.35     160 1598.61     163 1597.85     167 1596.95   171.9 1596.68
   188.4 1596.74   190.3  1597.1   192.7 1598.47   197.3 1604.38   199.7  1606.9
     202 1609.05   205.4 1611.47   218.6 1617.45   231.7 1622.81   236.9 1625.54
   249.3 1633.45   255.4  1638.4   267.1 1646.66     274 1651.89   285.8 1659.38
#Mann= 6 ,-1 , 0
       0      .1       0    10.7     .04       0    31.8    .035       0
     160      .1       0     163    .045       0   190.3      .1       0
#XS Ineff= 2 , 0
       0  124.84 1603.02               0
Permanent Ineff=
       F       F
Bank Sta=163,190.3
XS Rating Curve= 0 ,0
Exp/Cntr=0.3,0.1

Type RM Length L Ch R = 1 ,1488    ,136.6,137.2,137.3
XS GIS Cut Line= 3
 1994789.9999429177027.8142018621994678.88883176177034.064201877
1994422.63883173177239.619757429
#Sta/Elev= 30
       0 1658.08     6.3 1655.82      26 1647.37    39.2 1642.39    68.8 1629.56
    75.3 1623.75    78.6 1622.09    92.8 1620.63   121.7 1613.29   137.1 1608.41
   148.7 1603.51   166.2 1603.31   174.4 1600.62   176.7 1600.27   189.9 1599.93
   204.1 1598.58   241.9 1598.06   267.8 1598.45   281.8  1597.7   292.4 1596.92
     305 1596.97     3131594.818   321.8 1593.44   334.4 1594.87   341.71594.962
   347.2 1596.95   357.6  1604.2   396.1 1627.62     431 1646.71   439.8 1651.07
#Mann= 7 ,-1 , 0
       0      .1       0      26    .035       0   121.7     .04       0
   241.9    .035       0   281.8      .1       0     313    .045       0
   341.7      .1       0
#XS Ineff= 2 , 0
          303.38 1599.94
Permanent Ineff=
       F       F
Bank Sta=313,341.7
XS Rating Curve= 0 ,0
Exp/Cntr(USF)=0,0
Exp/Cntr=0.3,0.1

Type RM Length L Ch R = 1 ,1351    ,170.6,171.4,173.5
XS GIS Cut Line= 3
1994755.97216508176968.0919796381994524.72216511176987.536424085
1994339.99994287177129.203090772
#Sta/Elev= 30
       0 1640.25    21.6 1631.66    24.9 1629.25    31.5 1621.92      38 1621.12
    57.8 1621.02    84.3 1613.88   123.4 1609.55   156.6 1605.05   175.1 1604.12
   199.4 1599.81   215.8    1598   313.8 1594.47   328.6 1594.86   331.6 1594.28
   335.81592.211   339.8 1590.94     344 1590.63   356.4  1591.1   364.41592.465
   372.9 1594.58   384.7 1595.53   389.5 1596.91   405.8 1604.79   410.5 1607.81
   422.5 1619.03   426.8 1621.85   434.9 1624.93   443.2 1629.82   464.9 1636.24
#Mann= 6 ,-1 , 0
       0    .035       0      80     .06       0     180     .04       0
  292.07    .035       0   335.8    .045       0   364.4    .035       0
#XS Ineff= 2 , 0
           326.2 1595.95
Permanent Ineff=
       F       F
Bank Sta=335.8,364.4
XS Rating Curve= 0 ,0
Exp/Cntr(USF)=0,0
Exp/Cntr=0.3,0.1

Type RM Length L Ch R = 1 ,1180    ,242.8,244.8,238.7
XS GIS Cut Line= 4
1994560.23889038176812.0668784581994429.24457541176856.101692942
 1994228.8613047176990.9903234811994161.63372899177071.202814175
#Sta/Elev= 30
       0 1629.75    35.1 1618.96    51.5 1612.94    65.4 1609.31    68.9 1607.55
    75.8 1602.26    99.4 1601.45   103.5 1599.98   110.4 1595.34   120.8 1591.63
   130.3  1591.4   139.5 1595.43     146 1596.62   157.6  1595.9   177.6 1588.83
   234.21588.793   244.8 1587.89   251.31589.383   261.6 1591.38   308.8 1591.72
     349 1592.67   356.1 1593.59   363.5 1596.98   367.4  1600.2   372.7 1606.04
   380.2 1615.83   386.7 1621.43   393.7 1625.71     403 1628.63   484.4 1662.24
#Mann= 5 ,-1 , 0
       0     .04       0   198.2    .035       0   234.2    .045       0
   251.3    .035       0  449.75      .1       0
#XS Ineff= 2 , 0
          151.29 1601.88   262.2         1595.91
Permanent Ineff=
       F       F
Bank Sta=234.2,251.3
XS Rating Curve= 0 ,0
Exp/Cntr=0.3,0.1

Type RM Length L Ch R = 1 ,935     ,147.9,149.4,147.7
XS GIS Cut Line= 2
 1994413.7696389176604.538361112 1994112.5543611176905.753638888
#Sta/Elev= 30
       0 1641.46    16.6 1637.83    33.6 1629.72      46 1621.88    64.5 1611.75
    73.8 1600.93    75.4 1599.68    78.4 1598.71    88.5 1598.59    93.2 1597.55
    97.8 1593.93   103.2 1586.67   107.5 1582.75   110.9 1581.21     114 1580.84
   118.7 1580.98   123.3 1582.53   129.5    1585   189.8 1584.56   223.9 1587.64
     312 1587.31   366.9 1588.64   372.3 1589.93   378.5 1593.08   385.5 1599.73
   392.4 1604.95   398.6 1612.46   404.8 1616.99   409.5 1618.98     426 1622.96
#Mann= 5 ,-1 , 0
       0    .035       0      50     .04       0   107.5    .045       0
   123.3     .04       0     190    .035       0
#XS Ineff= 2 , 0
                          219.61         1592.38
Permanent Ineff=
       F       F
Bank Sta=107.5,123.3
XS Rating Curve= 0 ,0
Exp/Cntr(USF)=0,0
Exp/Cntr=0.3,0.1

Type RM Length L Ch R = 1 ,785     ,105.2,105.4,105.7
XS GIS Cut Line= 2
1994284.61799842176527.2933685331994031.14577621176789.446146294
#Sta/Elev= 30
       0 1627.61     7.7 1624.77    43.1 1607.29    46.7 1604.99    54.1 1598.44
    56.5 1596.93    75.1 1596.11    79.7 1593.56    88.9  1587.2    97.9 1582.99
   102.5 1579.54   107.5 1578.12   116.1 1578.55   119.1 1579.79   123.7 1581.55
   126.9 1581.97     140 1581.62   157.2 1582.27   177.1 1581.73   186.4 1584.77
   193.7 1585.72   216.5 1586.28   306.2 1586.09   334.9 1587.67   339.3 1588.35
   344.3 1590.27   348.9 1594.04   358.1 1604.49   360.4 1606.23   364.7 1608.25
#Mann= 5 ,-1 , 0
       0    .035       0      30     .04       0   102.5    .045       0
   119.1     .04       0     150    .035       0
#XS Ineff= 2 , 0
                           194.5         1589.34
Permanent Ineff=
       F       F
Bank Sta=102.5,119.1
XS Rating Curve= 0 ,0
Exp/Cntr(USF)=0,0
Exp/Cntr=0.3,0.1