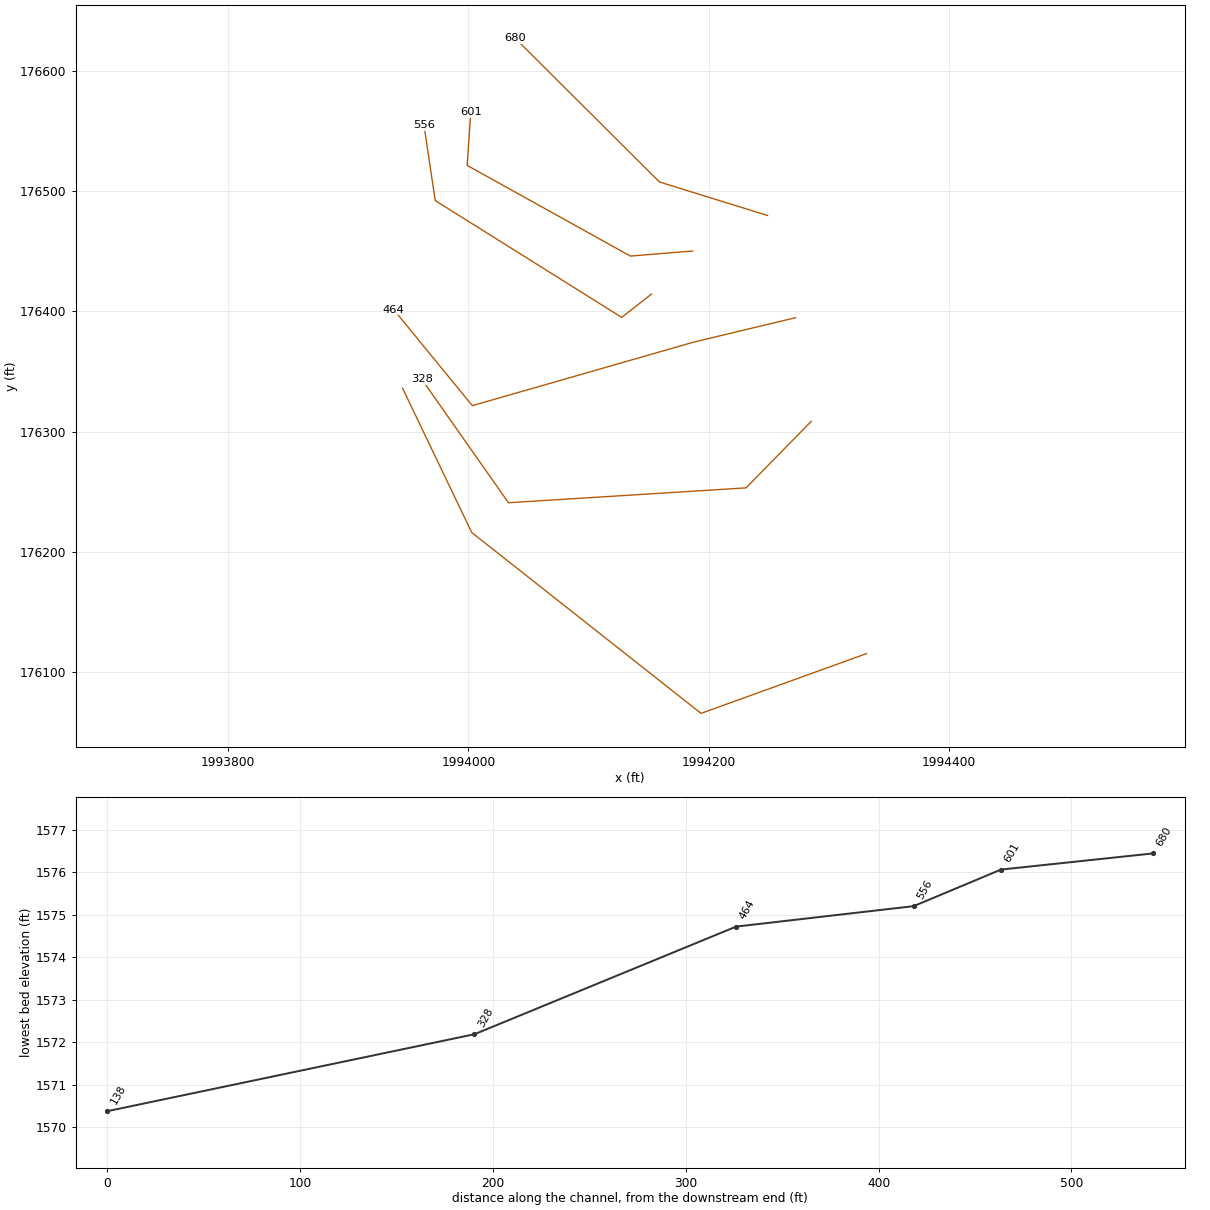
HEC-RAS study LKCKTRIB1.prj: LKCKTRIB1

--- LKCKTRIB1.g01 (geometry) --- (continued)

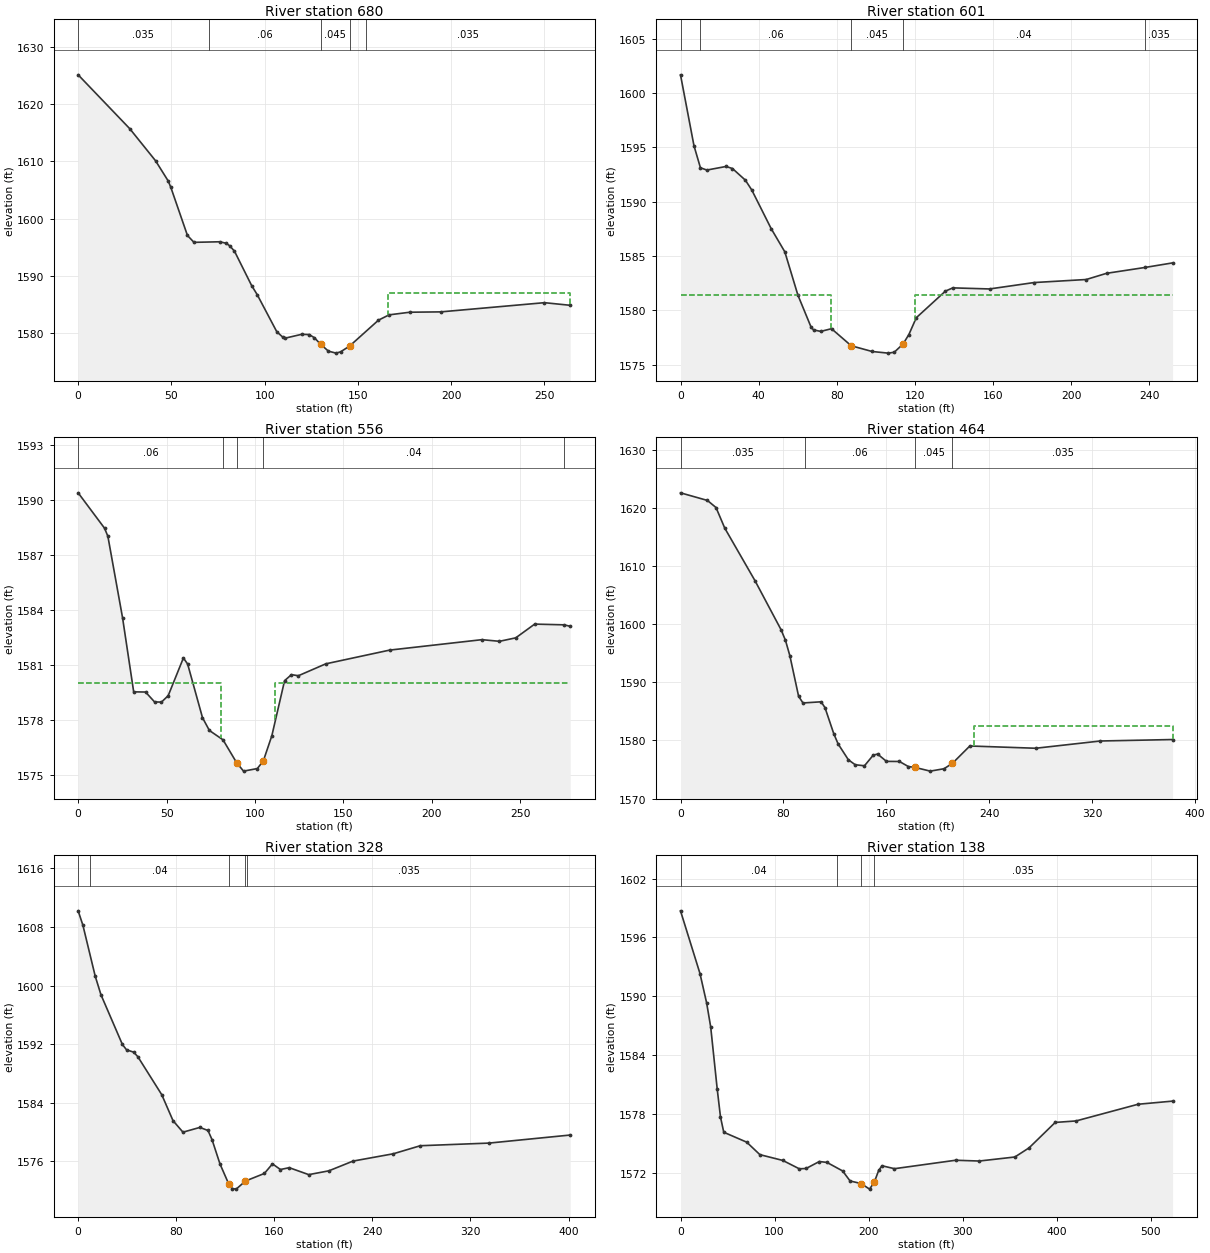
Type RM Length L Ch R = 1 ,680     ,75.5,78.9,82.1
XS GIS Cut Line= 3
1994249.15541344176479.9726703291994159.16278002176507.851708527
1994039.00610674176627.529443821
#Sta/Elev= 30
       0 1625.15    27.7 1615.71    41.5 1610.11    48.3 1606.56    49.7 1605.44
    58.6 1597.03    62.1 1595.83    75.8 1595.93    79.3 1595.68    81.2 1595.24
    83.8 1594.29      93 1588.27      96 1586.67   106.5 1580.18   109.9 1579.18
   111.1 1579.07   119.8 1579.73   123.9 1579.69   126.7 1579.12     1301577.985
   134.2 1576.78   138.3 1576.44   140.7 1576.67   145.51577.672     161 1582.21
   166.7 1583.14   177.8  1583.6   194.4 1583.66     250 1585.27   263.8 1584.81
#Mann= 5 ,-1 , 0
       0    .035       0      70     .06       0     130    .045       0
   145.5     .06       0  154.21    .035       0
#XS Ineff= 2 , 0
                          165.84         1587.02
Permanent Ineff=
       F       F
Bank Sta=130,145.5
XS Rating Curve= 0 ,0
Exp/Cntr(USF)=0,0
Exp/Cntr=0.5,0.3

Type RM Length L Ch R = 1 ,601     ,45.8,45.3,44.6
XS GIS Cut Line= 4
1994186.86481314176450.387959553  1994134.893584176446.157743228
1993998.92234498176521.6973204671994001.94392807176565.812433571
#Sta/Elev= 30
       0 1601.69     6.9 1595.16    10.2 1593.13    13.5 1592.92    23.3 1593.25
    26.6 1593.06    33.2 1591.99    36.5 1591.08    46.4 1587.53    53.4 1585.39
    60.1  1581.4    66.9 1578.43    68.1  1578.2    71.8 1578.06    77.3 1578.31
    87.41576.738    98.1 1576.21   106.3 1576.06   109.4 1576.14   113.91576.893
   116.9 1577.77   120.7 1579.32   135.6 1581.77   139.4 1582.07   158.2 1581.97
     181 1582.56   207.7 1582.84   218.1 1583.41   237.8 1583.95   251.9 1584.37
#Mann= 5 ,-1 , 0
       0    .035       0    10.2     .06       0    87.4    .045       0
   113.9     .04       0   237.8    .035       0
#XS Ineff= 2 , 0
              77 1581.45     120         1581.45
Permanent Ineff=
       F       F
Bank Sta=87.4,113.9
XS Rating Curve= 0 ,0
Exp/Cntr(USF)=0,0
Exp/Cntr=0.5,0.3

Type RM Length L Ch R = 1 ,556     ,82.1,92,103.3
XS GIS Cut Line= 4
1994152.41876592176414.4311207891994127.64178459176395.092989017
1993972.33241379176492.3879644981993962.96550621176555.236892758
#Sta/Elev= 30
       0  1590.4    14.9 1588.47    16.8 1588.03    25.1 1583.58    31.4 1579.53
    38.1 1579.52    43.2 1578.98    47.1 1578.97    50.9 1579.32    59.5 1581.38
    61.9 1581.05    70.3 1578.12    74.2 1577.42    81.9 1576.91    89.6 1575.66
    93.5  1575.2   101.3 1575.34   104.7 1575.76   109.5 1577.13   116.7 1580.14
   120.6 1580.47   124.5 1580.41     140 1581.06   176.1 1581.81   228.3 1582.38
   238.2 1582.29   247.4 1582.48   258.1 1583.23   274.7 1583.19   278.2 1583.11
#Mann= 5 ,-1 , 0
       0     .06       0    81.9     .04       0    89.6    .045       0
   104.7     .04       0   274.7    .035       0
#XS Ineff= 2 , 0
            80.5    1580   111.5            1580
Permanent Ineff=
       F       F
Bank Sta=89.6,104.7
XS Rating Curve= 0 ,0
Exp/Cntr(USF)=0,0
Exp/Cntr=0.5,0.3

Type RM Length L Ch R = 1 ,464     ,134.8,135.7,137.6
XS GIS Cut Line= 4
1994272.50043033176394.8307746151994187.73679549176374.513794074
1994003.23261287176321.551789172 1993937.7687096176401.552864404
#Sta/Elev= 30
       0 1622.65    20.9 1621.34    27.6 1620.12    34.4 1616.57      58 1607.48
    78.2 1599.06    81.6 1597.24      85  1594.6    91.8 1587.61    95.2 1586.46
   109.3 1586.66   112.3 1585.66   119.1 1581.19   122.5 1579.41   130.5 1576.67
   135.8 1575.82     143 1575.64   149.8 1577.47   153.2 1577.66   160.1  1576.4
   170.2 1576.38   177.1 1575.51   182.31575.359   194.1 1574.72   204.8 1575.13
   211.3 1576.05   224.9 1579.05   276.1 1578.66   326.4 1579.91   382.5 1580.16
#Mann= 4 ,-1 , 0
       0    .035       0   97.16     .06       0   182.3    .045       0
   211.3    .035       0
#XS Ineff= 2 , 0
                          227.86         1582.49
Permanent Ineff=
       F       F
Bank Sta=182.3,211.3
XS Rating Curve= 0 ,0
Exp/Cntr(USF)=0,0
Exp/Cntr=0.3,0.1

Type RM Length L Ch R = 1 ,328     ,196.2,190.5,181.8
XS GIS Cut Line= 4
1994285.51760503 176308.468508661994231.23296796176253.063871077
1994033.36413364176240.6728053841993961.19430546176343.398755245
#Sta/Elev= 30
       0 1610.21     3.9 1608.23    13.9  1601.3    18.6 1598.75    36.1 1591.95
    39.5 1591.22    45.3  1590.9    48.7 1590.28    68.2 1585.09    77.4 1581.54
    85.5 1579.97    99.3 1580.62   105.9  1580.2   109.2 1578.96   115.7 1575.63
   122.81572.906   125.6 1572.27   128.9 1572.19   136.51573.298   151.9 1574.33
   158.5 1575.64     165 1574.87   172.2 1575.12   188.1 1574.17   204.5 1574.69
   224.2 1576.02   257.1 1577.02   279.1 1578.12   335.2 1578.48   401.4 1579.58
#Mann= 5 ,-1 , 0
       0    .035       0      10     .04       0   122.8    .045       0
   136.5     .04       0  137.57    .035       0
Bank Sta=122.8,136.5
XS Rating Curve= 0 ,0
Exp/Cntr(USF)=0,0
Exp/Cntr=0.3,0.1

Type RM Length L Ch R = 1 ,138     ,,,
XS GIS Cut Line= 4
1994331.56619972176114.9993573211994193.77814233176065.226363268
1994002.74338959176215.8844368471993945.08817612176336.160265353
#Sta/Elev= 30
       0 1598.71    20.7 1592.33    27.8 1589.33    32.1 1586.89      39  1580.6
    42.5 1577.73      46 1576.17    70.4 1575.16    84.4 1573.89   108.8  1573.3
   126.3 1572.45   133.5 1572.48   147.6 1573.19   155.7  1573.1   172.4 1572.23
   180.3 1571.21     192 1570.95     201 1570.38     206 1571.08   210.7 1572.28
   214.2 1572.76   227.5 1572.46   292.5 1573.32   317.6 1573.24   355.5 1573.65
   370.6 1574.58   398.4 1577.17   420.5 1577.32   486.5 1579.02   523.2 1579.34
#Mann= 4 ,-1 , 0
       0     .04       0   166.5    .035       0     192    .045       0
     206    .035       0
#XS Ineff= 2 , 0
           51.66    1574
Permanent Ineff=
       F       F
Bank Sta=192,206
XS Rating Curve= 0 ,0
Exp/Cntr(USF)=0,0
Exp/Cntr=0.3,0.1
LCMann Table=0

Chan Stop Cuts=-1
Use User Specified Reach Order=0
Composite Channel Slope=5